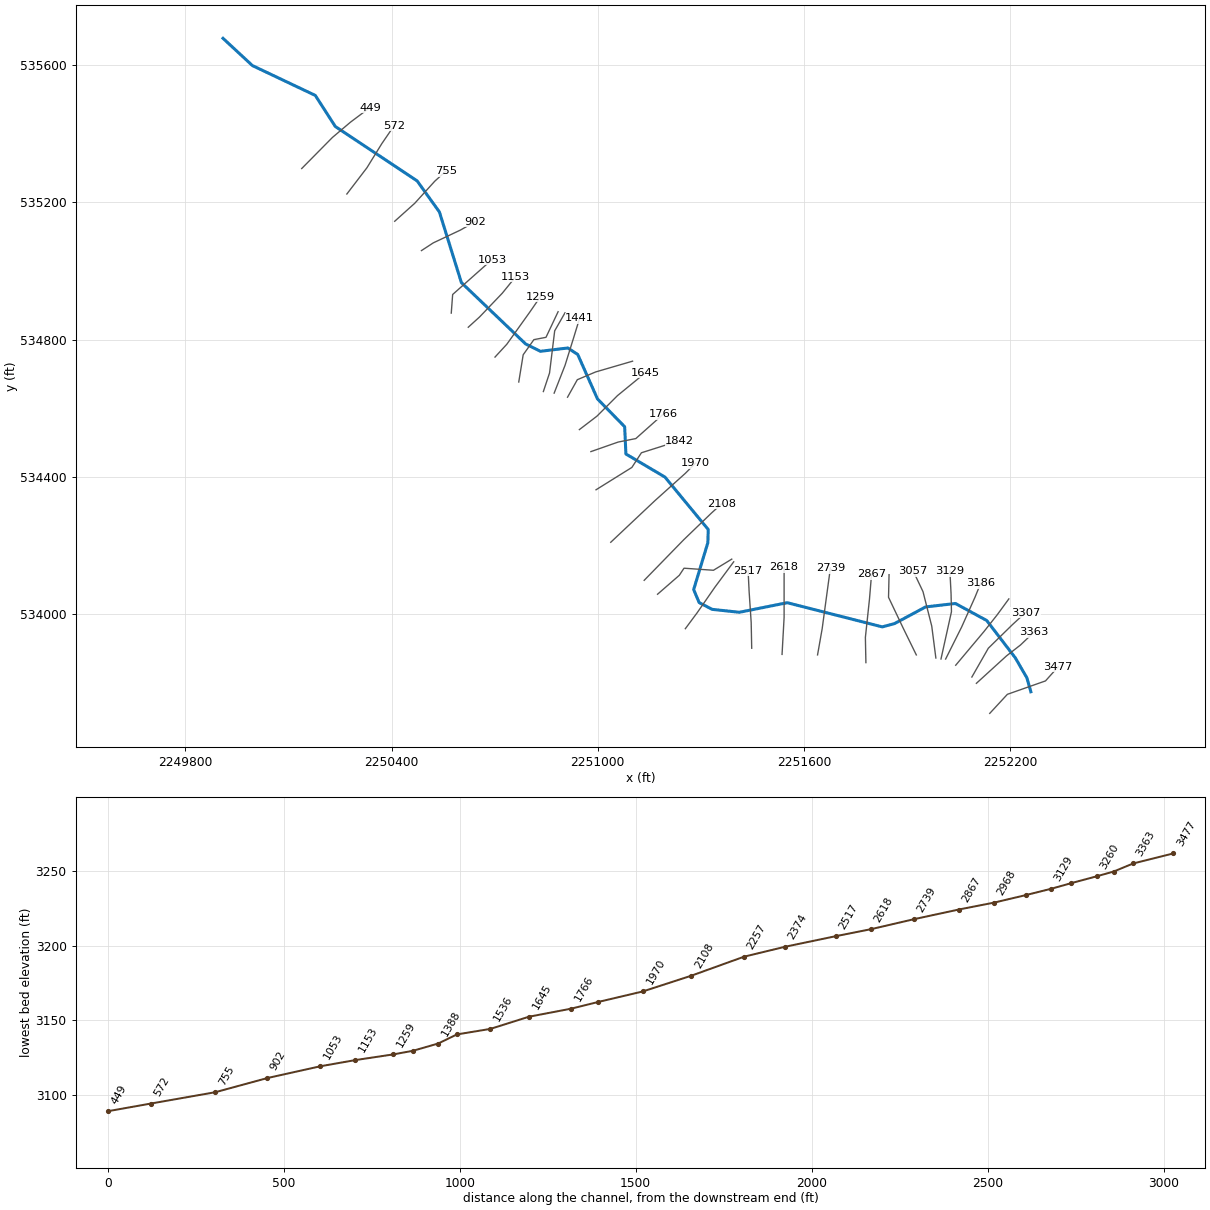
--- TYGRTVALRV.prj (project) ---

Proj Title=TYGRTVALRV
Current Plan=p01
Default Exp/Contr=0,0
English Units
Geom File=g01
Flow File=f01
Plan File=p01
Background Map Layer=Inundation Boundary (01pct Value_0)
BEGIN DESCRIPTION:
----------MODEL BY WOOD PLC 2021----------
Stream Name: Tygart Valley River
Flood Zone: Approximate
Pocahontas County, WV
HEC-RAS Version: RAS 6.0
Vertical Datum: NAVD88
Projection: NAD 1983 StatePlane West Virginia S FIPS 4702 (US Feet)
Terrain: 1-meter LIDAR (FEMA Region III 3DEP collected 2016-2018)
Land Use: 2019 NLCD
Hydrologic Method:
WV 2010 Regional Regression Equations
Model Notes:
Model extends beyond county boundary into Randolph County on the downstream end
END DESCRIPTION:
DSS Export Rating Curves= 0
DSS Export Rating Curve Sorted= 0
DSS Export Volume Flow Curves= 0
DXF OffsetX= 0
DXF OffsetY= 0
DXF ScaleX= 0
DXF ScaleY= 0

--- TYGRTVALRV.p01 (plan) ---

Plan Title=Floodplain
Program Version=6.00
Short Identifier=Floodplain
Geom File=g01
Flow File=f01
Subcritical Flow
K Sum by GR= 0
Std Step Tol= 0.01
Critical Tol= 0.01
Num of Std Step Trials= 20
Max Error Tol= 0.3
Flow Tol Ratio= 0.001
Split Flow NTrial= 30
Split Flow Tol= 0.02
Split Flow Ratio= 0.02
Log Output Level= 0
Friction Slope Method= 1
Unsteady Friction Slope Method= 2
Unsteady Bridges Friction Slope Method= 1
Parabolic Critical Depth
Global Vel Dist= 0 , 0 , 0
Global Log Level= 0
CheckData=True
Encroach Param=-1 ,0,0, 0
Mapping Interval=1HOUR
Computation Time Step Use Courant=        0
Computation Time Step Use Time Series=    0
Computation Time Step Count To Double=0
Computation Time Step Max Doubling=0
Computation Time Step Max Halving=0
Computation Time Step Residence Courant=0
Run HTab= 0
Run UNet= 0
Run Sediment= 0
Run PostProcess= 0
Run WQNet= 0
Run RASMapper=-1
UNET Theta= 0
UNET Theta Warmup= 0
UNET ZTol= 0
UNET ZSATol= 0
UNET MxIter= 0
UNET Max Iter WO Improvement= 0
UNET MaxInSteps= 0
UNET DtIC= 0
UNET DtMin= 0
UNET MaxCRTS= 0
UNET WFStab= 0
UNET SFStab= 0
UNET WFX= 1
UNET SFX= 1
UNET Gravity=32.174
UNET 1D Methodology=Finite Difference
UNET DSS MLevel= 1
UNET Pardiso=0
UNET DZMax Abort= 0
UNET Use Existing IB Tables= 0
UNET Froude Reduction=False
UNET Froude Limit= 0
UNET Froude Power= 0
UNET D1 Cores= 0
UNET WindReference=Eulerian
UNET WindDragFormulation=Hsu (1988)
UNET D2 Coriolis=0
UNET D2 Cores= 0
UNET D2 Theta= 1
UNET D2 Theta Warmup= 1
UNET D2 Z Tol= 0.01
UNET D2 Volume Tol= 0.01
UNET D2 Max Iterations= 20
UNET D2 Equation= 0
UNET D2 RampUpFraction=0.1
UNET D2 TimeSlices= 1
UNET D2 Turbulence Formulation=Non-Conservative (original)
UNET D2 Eddy Viscosity=0.3
UNET D2 Transverse Eddy Viscosity=0.1
UNET D2 Smagorinsky Mixing=0
UNET D2 BCVolumeCheck=0
UNET D2 Cores=0
UNET D2 SolverType=PARDISO (Direct)
UNET D2 Minimum Iterations= 2147483647
UNET D2 Maximum Iterations= 2147483647
UNET D2 Restart Number= 10
UNET D2 Relaxation Coeff=1.3
UNET D2 SOR Precondition Iterations= 10
UNET D2 ILUT Maximum Fill= 8
UNET D2 ILUT Tolerance=1E-08
UNET D1D2 MaxIter= 0
UNET D1D2 ZTol=0.01
UNET D1D2 QTol=0.1
UNET D1D2 MinQTol=1
Write IC File= 0
Write IC File at Fixed DateTime=0
Write IC File at Sim End=0
Echo Input=False
Echo Parameters=False
Echo Output=False
Write Detailed= 0
HDF Write Warmup=0
HDF Write Time Slices=0
HDF Flush=0
HDF Compression= 1
HDF Chunk Size= 1
HDF Spatial Parts= 1
HDF Use Max Rows=0
HDF Fixed Rows= 1
Calibration Method= 0
Calibration Iterations= 20
Calibration Max Change=0.05
Calibration Tolerance=0.2
Calibration Maximum=1.5
Calibration Minimum=0.5
Calibration Optimization Method= 1
WQ AD Non Conservative
WQ ULTIMATE=-1
WQ Max Comp Step=1HOUR
WQ Output Interval=15MIN
WQ Output Selected Increments= 0
WQ Output face flow=0
WQ Output face velocity=0
WQ Output face area=0
WQ Output face dispersion=0
WQ Output cell volume=0
WQ Output cell surface area=0
WQ Output cell continuity=0
WQ Output cumulative cell continuity=0
WQ Output face conc=0
WQ Output face dconc_dx=0
WQ Output face courant=0
WQ Output face peclet=0
WQ Output face adv mass=0
WQ Output face disp mass=0
WQ Output cell mass=0
WQ Output cell source sink temp=0
WQ Output nsm pathways=0
WQ Output nsm derived pathways=0
WQ Create Restart=0
WQ Fixed Restart=0
WQ System Summary=0
WQ Write To DSS=0
Sorting and Armoring Iterations= 10
XS Update Threshold= 0.02
Bed Roughness Predictor= 0
Hydraulics Update Threshold= 0.02
Energy Slope Method= 1
Volume Change Method= 1
Sediment Retention Method= 0
Sediment TS Multiplier= 1
Warm Up Method= 0
XS Weighting Method= 0
Number of US Weighted Cross Sections= 1
Number of DS Weighted Cross Sections= 1
Upstream XS Weight=0
Main XS Weight=1
Downstream XS Weight=0
Number of DS XS's Weighted with US Boundary= 1
Upstream Boundary Weight= 1
Weight of XSs Associated with US Boundary= 0
Number of US XS's Weighted with DS Boundary= 1
Downstream Boundary Weight= 0.5
Weight of XSs Associated with DS Boundary= 0.5
Percentile Method= 0
Sediment Output Level= 3
Mass or Volume Output= 0
Output Increment Type= 1
Profile and TS Output Increment= 1
Transport Output Increment 1
XS Output Flag= 0
XS Output Increment= 10
Read HDF5 Sediment Hotstart= 0
Sediment Hotstart Type= 0
Write Gradation File= 0
Read Gradation Hotstart= 0
Write HDF5 File= 1
Write Binary Output= 1
Write DSS Sediment File= 0
DSS Sediment Output Type= 1
SV Curve= 0
Specific Gage Flag= 0
Subcell Erosion Methods= 0
Subcell Deposition Methods= 0
Advection Scheme= 1
Matrix Solver= 0
Implicit Weighting Factor= 1
Maximum Outer Loop Convergence Iterations= 5
Convergence Maximum Absolute= 0.001
Convergence RMSE= 0.0001
Grain Fractions Max Abs Error= 0.001
Max Subgrid Regions= 1
Max Subgrid Length Scale= 3.402823E+38
Initial Layer Thickness= 3.402823E+38
Min Layer Thickness= 3.402823E+38
Max Layer Thickness= 3.402823E+38
Number of Layers= 5

--- TYGRTVALRV.f01 (steady flow) ---

Flow Title=Flow
Program Version=6.10
Number of Profiles= 6
Profile Names=01pct,10pct,04pct,02pct,0_2pct,01plus
River Rch & RM=TYGRTVALRV,Main            ,3477
     631     335     444     534     880     933
River Rch & RM=TYGRTVALRV,Main            ,572
     761     406     538     646    1057    1125
Boundary for River Rch & Prof#=TYGRTVALRV,Main            , 1
Up Type= 0
Dn Type= 1
Dn Known WS=3072.7
Boundary for River Rch & Prof#=TYGRTVALRV,Main            , 2
Up Type= 0
Dn Type= 1
Dn Known WS=3071.8
Boundary for River Rch & Prof#=TYGRTVALRV,Main            , 3
Up Type= 0
Dn Type= 1
Dn Known WS=3072.1
Boundary for River Rch & Prof#=TYGRTVALRV,Main            , 4
Up Type= 0
Dn Type= 1
Dn Known WS=3072.4
Boundary for River Rch & Prof#=TYGRTVALRV,Main            , 5
Up Type= 0
Dn Type= 1
Dn Known WS=3073.4
Boundary for River Rch & Prof#=TYGRTVALRV,Main            , 6
Up Type= 0
Dn Type= 1
Dn Known WS=3073.5
DSS Import GetInterval= 0
DSS Import GetPeak= 0
DSS Import FillOption= 0

--- TYGRTVALRV.g01 (geometry) ---

Geom Title=Geometry
Program Version=6.00

River Reach=TYGRTVALRV      ,Main
Reach XY= 30
     2252259.895      533775.087     2252248.372      533815.659
     2252214.796      533873.676     2252131.543       533982.45
     2252040.378      534031.972     2251953.736      534022.007
     2251863.391      533973.545     2251827.683      533963.932
      2251551.27      534034.231     2251411.792      534006.371
     2251332.544      534014.939     2251294.803      534034.656
2251278.91554411534072.396461594     2251320.228      534209.022
     2251321.264      534247.207     2251195.404       534399.75
     2251081.771      534466.959     2251078.162      534546.267
     2250999.026      534627.217     2250941.681       534756.35
     2250912.806      534775.366     2250833.141      534765.712
     2250790.099       534786.99     2250603.148      534965.512
     2250539.227      535170.948     2250474.376      535261.484
     2250236.355       535419.68     2250178.161      535510.098
     2249995.137      535596.976     2249909.618      535676.228

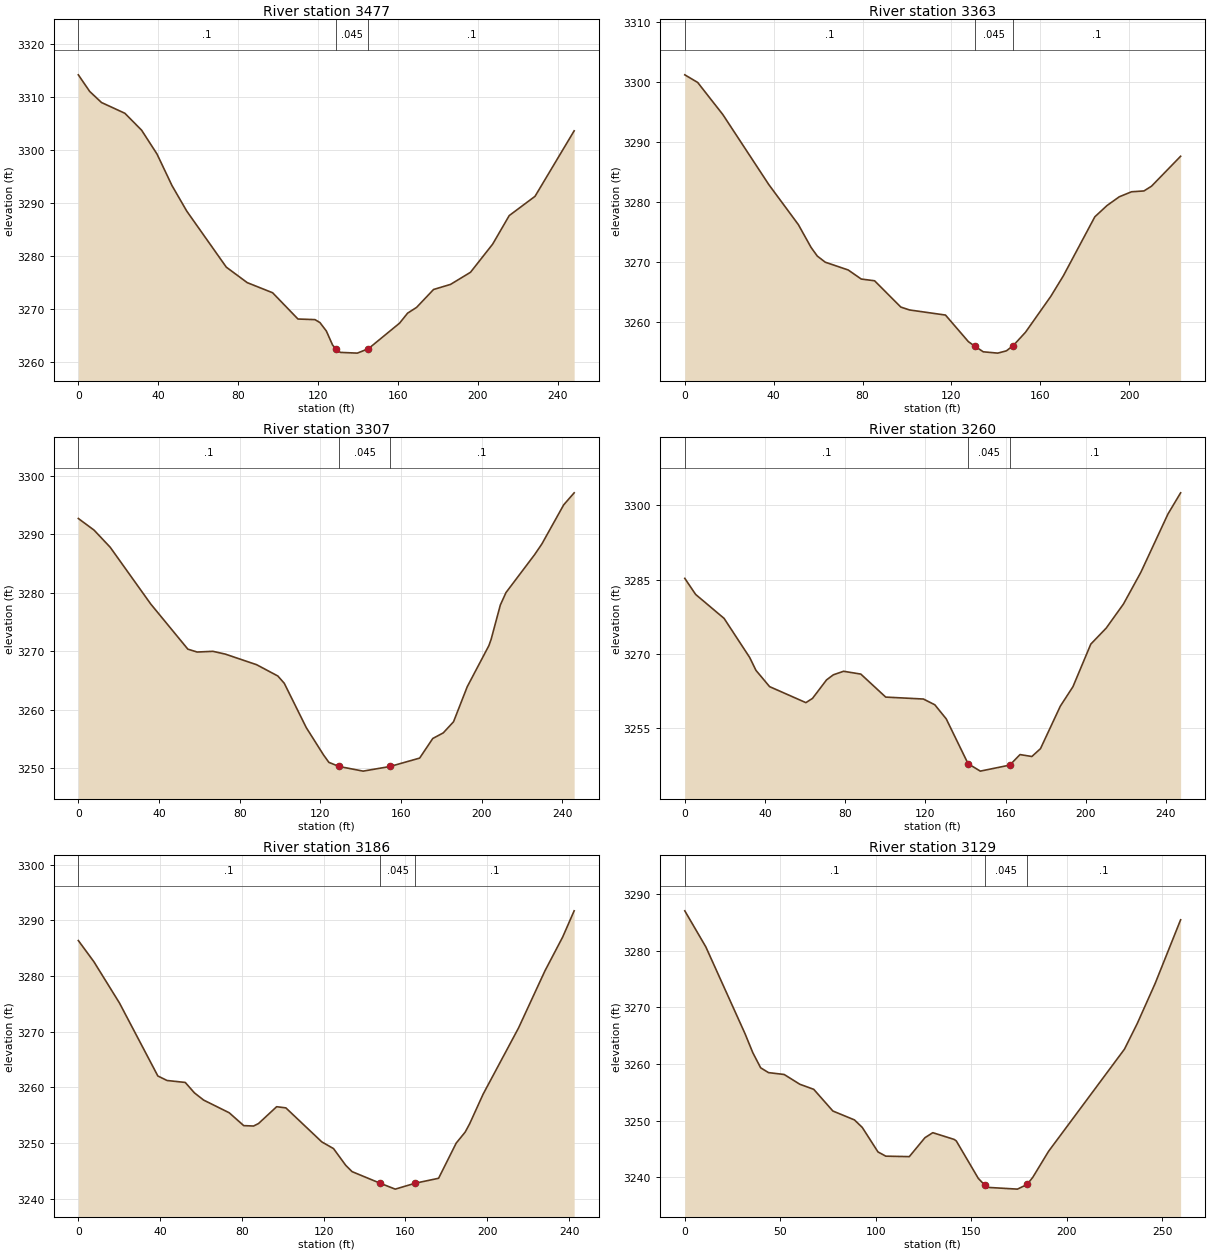
Type RM Length L Ch R = 1 ,3477    ,108.6,114.4,118.2
XS GIS Cut Line= 4
2252140.32069359533712.2774731762252191.64521525533767.707956571
2252302.50618204533806.7145930332252339.45983764533847.774210363
#Sta/Elev= 30
       0 3314.16     5.7 3311.02    11.6 3308.93    23.3  3306.9    31.7  3303.7
    39.4  3299.2    46.9 3293.25    54.3 3288.42    74.1 3277.84    84.6 3274.91
    97.3    3273     110 3268.04   118.5 3267.93     121 3267.37   124.2 3265.78
   127.3 3263.15  128.933262.431   131.2 3261.74   139.7  3261.6  145.26 3262.43
   160.9 3267.27   164.9 3269.15   169.4 3270.24   177.9 3273.62   186.4 3274.58
   196.4 3276.87   207.5 3282.19   215.8 3287.58   228.7 3291.21248.3061 3303.58
#Mann= 3 ,-1,0
       0      .1       0  128.93    .045       0  145.26      .1       0
Bank Sta=128.93,145.26
XS Rating Curve= 0 ,0
Exp/Cntr(USF)=0,0
Exp/Cntr=0.3,0.1

Type RM Length L Ch R = 1 ,3363    ,53.9,55.3,57.2
XS GIS Cut Line= 4
2252101.47326334533799.699748995 2252189.0029577533879.435703447
2252229.77021261533911.210181536 2252268.1393937533947.780807262
#Sta/Elev= 30
       0 3301.15     5.8 3299.88    17.1 3294.55    37.8  3282.9    51.1 3276.24
    56.8 3272.46    59.6 3271.02    63.2 3269.99    73.5  3268.7    79.4 3267.19
    85.4  3266.9    97.2 3262.53   101.1 3262.05   117.3  3261.2   127.6 3256.78
   130.5 3256.02   134.3 3255.09   140.8 3254.87   144.7 3255.25   147.8 3256.13
   153.3 3258.34   164.7 3264.32   170.4 3267.77   184.5 3277.54     190 3279.42
   195.5 3280.87     201  3281.7   206.6 3281.84     210 3282.63   223.1 3287.61
#Mann= 3 ,-1,0
       0      .1       0   130.5    .045       0   147.8      .1       0
Bank Sta=130.5,147.8
XS Rating Curve= 0 ,0
Exp/Cntr(USF)=0,0
Exp/Cntr=0.3,0.1

Type RM Length L Ch R = 1 ,3307    ,44.9,47.3,48.6
XS GIS Cut Line= 4
2252088.32279421533817.9977758752252136.21473186533901.808666768
2252206.55601529533970.6533271442252243.97159158534005.075657332
#Sta/Elev= 30
       0 3292.71     7.8 3290.72    15.8 3287.79    35.9 3278.08    54.3 3270.36
    58.9 3269.87    66.7 3269.99    72.8 3269.52    88.4  3267.7    98.9 3265.77
   102.1 3264.52     113 3256.94   121.5  3252.3   124.2    3251  129.213250.298
   141.2  3249.5  154.583250.298   169.2 3251.73   175.7 3255.08   180.9 3256.04
     186 3257.94   192.8 3263.94   203.5 3270.95   204.6    3272   209.2 3277.91
     212 3280.04   226.2 3286.53   229.8 3288.36   240.6 3295.04245.7954  3297.1
#Mann= 3 ,-1,0
       0      .1       0  129.21    .045       0  154.58      .1       0
Bank Sta=129.21,154.58
XS Rating Curve= 0 ,0
Exp/Cntr(USF)=0,0
Exp/Cntr=0.3,0.1

Type RM Length L Ch R = 1 ,3260    ,69.3,73.8,76.3
XS GIS Cut Line= 4
2252041.32730351533852.3864358252252123.67858461533950.531113303
2252162.03397581533999.0394021712252195.87696804534045.291491556
#Sta/Elev= 30
       0 3285.26     5.4 3282.02    19.6 3277.18    32.4 3269.27    35.5 3266.69
    42.3 3263.41    60.4 3260.18    63.7 3261.04    70.7 3264.77    74.1  3265.8
    79.2 3266.51    87.8 3265.94   100.2  3261.3     119 3260.91   124.7 3259.75
   130.4  3256.9   141.33247.854   147.4 3246.36   162.1 3247.58   167.2  3249.7
   173.1 3249.31   177.4 3250.89   187.3 3259.47   193.6  3263.4   202.5 3271.99
   210.2 3275.23   218.8 3280.09   227.5 3286.51     241 3298.26   247.3 3302.52
#Mann= 3 ,-1,0
       0      .1       0   141.3    .045       0   162.1      .1       0
Bank Sta=141.3,162.1
XS Rating Curve= 0 ,0
Exp/Cntr(USF)=0,0
Exp/Cntr=0.3,0.1

Type RM Length L Ch R = 1 ,3186    ,50.2,56.9,64.5
XS GIS Cut Line= 4
2252011.99501857533870.3795826832252058.39033317533963.170211886
2252097.30253252534049.9743488822252113.76538609534090.383171276
#Sta/Elev= 30
       0 3286.37     7.6 3282.57    20.1 3275.16    38.9 3262.03    43.4 3261.22
    52.3 3260.87    56.8 3258.99    61.3  3257.7    73.8 3255.42    80.9 3253.11
    85.7 3253.04    88.1 3253.48      97 3256.51   101.5  3256.3   119.1 3250.18
   124.8 3248.99   130.8 3245.97   133.9 3244.84  147.613242.759     155  3241.7
  164.733242.759   176.2 3243.65   184.8 3249.96   189.2 3251.95   191.4 3253.45
     198 3258.78   215.3 3270.66   228.2 3280.91   236.9 3287.01242.5036 3291.71
#Mann= 3 ,-1,0
       0      .1       0  147.61    .045       0  164.73      .1       0
Bank Sta=147.61,164.73
XS Rating Curve= 0 ,0
Exp/Cntr(USF)=0,0
Exp/Cntr=0.3,0.1

Type RM Length L Ch R = 1 ,3129    ,69.7,72.2,76.2
XS GIS Cut Line= 4
2251998.45951335533870.4360316832252028.91820636  534008.0642001
2252027.79010662534059.9567881912252024.40580739534126.514672917
#Sta/Elev= 30
       0    3287      11 3280.65    31.5 3265.36    35.6 3261.99    39.7 3259.33
    43.8 3258.48      52 3258.15    60.2 3256.43    67.5 3255.53    77.5 3251.71
    88.8 3250.14    92.9 3248.81   101.1  3244.5   105.2 3243.75   117.5 3243.67
   125.7 3247.01   129.8 3247.89     141  3246.7   142.1 3246.43   153.6 3239.84
   156.93238.679   158.4 3238.25   174.1 3237.94  179.14 3238.76   182.1 3240.01
   190.4 3244.61   230.1 3262.61   236.8 3267.13   246.2 3274.22   259.5 3285.42
#Mann= 3 ,0,0
       0      .1       0   156.9    .045       0  179.14      .1       0
Bank Sta=156.9,179.14
XS Rating Curve= 0 ,0
Exp/Cntr(USF)=0,0
Exp/Cntr=0.3,0.1

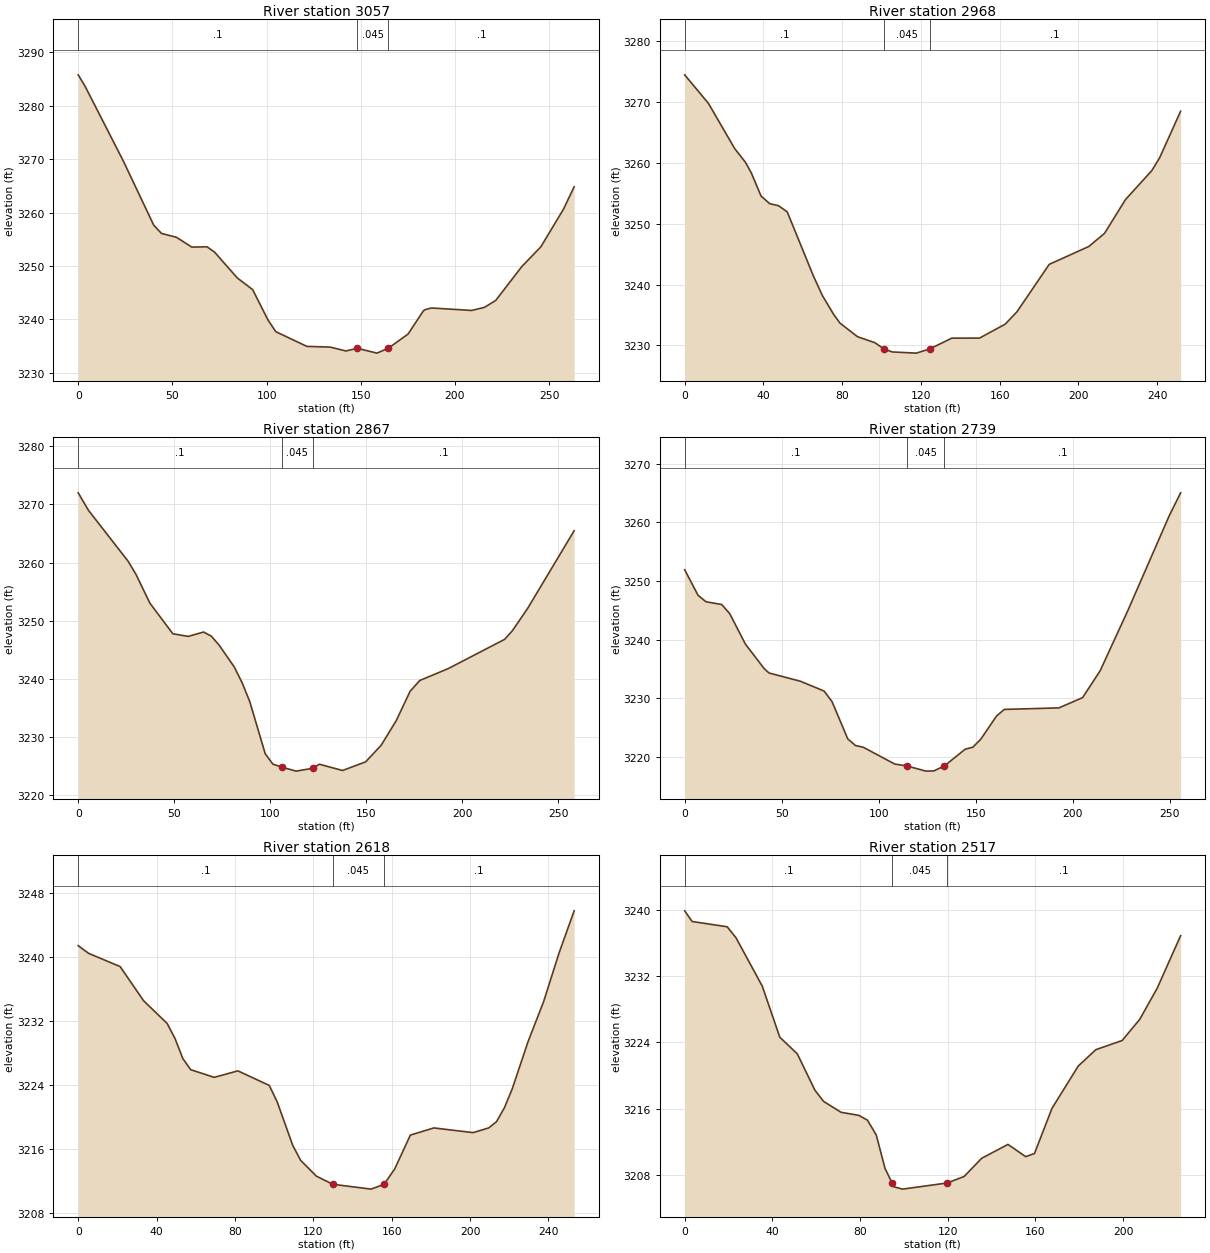
Type RM Length L Ch R = 1 ,3057    ,88.3,89.6,92.9
XS GIS Cut Line= 4
2251983.55918059533873.3728287862251971.58619618533966.163457989
 2251946.1436043 534066.437202452251917.70776632534126.302124516
#Sta/Elev= 30
       0 3285.74     3.8  3283.5      24 3269.59    40.1 3257.63    44.2 3256.09
    52.2 3255.36    60.3 3253.53    68.4 3253.59    72.4 3252.59    84.5 3247.75
    92.6 3245.59   100.8 3239.88   104.9 3237.72   121.4 3234.97   133.8 3234.84
   142.1 3234.11   148.2 3234.61   158.6 3233.71  164.673234.632   175.1 3237.27
   183.3 3241.64   184.4 3241.86   187.5 3242.15   208.9 3241.69   215.6 3242.26
   221.6 3243.54   235.5 3249.89   245.6 3253.58   257.6 3260.61263.2863  3264.8
#Mann= 3 ,-1,0
       0      .1       0   148.2    .045       0  164.67      .1       0
Bank Sta=148.2,164.67
XS Rating Curve= 0 ,0
Exp/Cntr(USF)=0,0
Exp/Cntr=0.3,0.1

Type RM Length L Ch R = 1 ,2968    ,107.7,100.3,90.9
XS GIS Cut Line= 4
2251926.68750463533882.3525670962251889.27192834533958.680342731
2251845.86985984534049.9743488822251847.36648289534115.825763155
#Sta/Elev= 30
       0 3274.44    12.1 3269.74    25.4 3262.33    30.9 3260.06    33.9  3258.3
    38.8 3254.53    43.2 3253.28    47.7 3252.94    52.1 3251.93    65.5 3241.33
      70 3238.17    75.7 3235.08    78.9 3233.66    87.8 3231.43    96.6 3230.45
   101.33229.407   105.5 3228.92   117.7 3228.73   124.43229.407   135.7 3231.19
   149.8  3231.2   162.8 3233.48   168.8 3235.51   185.2 3243.31   205.3 3246.24
   213.3  3248.4   223.9 3253.93   237.3  3258.7   241.3 3260.81251.9592 3268.46
#Mann= 3 ,-1,0
       0      .1       0   101.3    .045       0   124.4      .1       0
Bank Sta=101.3,124.4
XS Rating Curve= 0 ,0
Exp/Cntr(USF)=0,0
Exp/Cntr=0.3,0.1

Type RM Length L Ch R = 1 ,2867    ,128,128.2,127.6
XS GIS Cut Line= 4
2251780.01844557533859.9032213222251778.52182251533933.237750853
2251790.49480693534045.4844797272251796.48129913534117.322386206
#Sta/Elev= 30
       0 3271.99     5.3    3269      26 3260.22    30.1 3257.96    37.3 3253.03
    49.3 3247.74    57.3 3247.29    65.3 3248.04    69.3 3247.34    73.3 3245.83
    81.3 3242.03    85.4  3239.3    89.4 3236.03    97.4 3227.11   101.4 3225.31
  105.993224.805   113.5 3224.11   122.1  3224.6   125.6  3225.3   137.7 3224.22
   149.7  3225.7   157.8 3228.56   165.7 3232.83   172.9 3237.86   177.9  3239.7
   192.8 3241.76   222.1 3246.78   226.1 3248.24   234.1 3252.11258.3202 3265.47
#Mann= 3 ,-1,0
       0      .1       0  105.99    .045       0   122.1      .1       0
Bank Sta=105.99,122.1
XS Rating Curve= 0 ,0
Exp/Cntr(USF)=0,0
Exp/Cntr=0.3,0.1

Type RM Length L Ch R = 1 ,2739    ,116.8,120.9,122
XS GIS Cut Line= 4
2251639.33587871533882.3525670962251652.80548618533958.680342731
2251667.77171669534069.430448553  2251676.751455534135.281862826
#Sta/Elev= 30
       0 3251.93     6.9 3247.57      11 3246.47    19.1    3246    23.2 3244.46
    31.3 3239.26    41.1 3235.03    43.5 3234.33    59.7 3232.92    71.9 3231.25
      76 3229.44    84.1 3223.09    88.1 3221.96    92.1 3221.67   108.3 3218.81
  114.583218.487   124.4  3217.6   128.5 3217.64  133.923218.487   144.6 3221.33
   148.6 3221.68   152.7 3223.05   160.8 3226.99   164.8 3228.12     193 3228.38
   205.2 3230.13   214.3 3234.75   228.5 3244.96   249.8 3261.09255.7248 3265.04
#Mann= 3 ,-1,0
       0      .1       0  114.58    .045       0  133.92      .1       0
Bank Sta=114.58,133.92
XS Rating Curve= 0 ,0
Exp/Cntr(USF)=0,0
Exp/Cntr=0.3,0.1

Type RM Length L Ch R = 1 ,2618    ,98.4,101.1,100.9
XS GIS Cut Line= 4
2251536.06888815533883.8491901482251542.05538035533991.606049867
2251542.05538035534094.8730404312251542.05538035534136.778485878
#Sta/Elev= 30
       0 3241.46     5.3  3240.5    21.4 3238.84    33.4 3234.56    45.4 3231.72
    49.4 3229.84    53.4 3227.33    57.4 3225.94    69.4 3224.98    81.5 3225.79
    97.5 3223.97   101.5 3221.94   109.5 3216.46   113.5  3214.6   121.5 3212.62
   129.93211.599   149.5 3210.99  156.113211.599   161.5 3213.51   169.5 3217.75
   181.5 3218.65   201.5 3218.06   209.5 3218.65   213.5 3219.44   217.5 3221.17
   221.5 3223.54   229.5  3229.4   237.5 3234.45   245.5 3240.62253.0955 3245.82
#Mann= 3 ,-1,0
       0      .1       0   129.9    .045       0  156.11      .1       0
Bank Sta=129.9,156.11
XS Rating Curve= 0 ,0
Exp/Cntr(USF)=0,0
Exp/Cntr=0.3,0.1

Type RM Length L Ch R = 1 ,2517    ,153.1,143.1,134.6
XS GIS Cut Line= 4
 2251447.7681281533901.8086667682251446.27150505533976.639819351
2251440.28501284 534066.437202452251437.29176674534127.798747568
#Sta/Elev= 30
       0 3239.93     3.4 3238.64    19.4    3238    23.4 3236.68    35.4 3230.82
    43.4 3224.64    51.4 3222.62    59.4 3218.24    63.4 3216.87    71.4 3215.55
    79.4 3215.19    83.4  3214.6    87.4 3212.82    91.4 3208.78   94.623206.999
    95.4 3206.55    99.4 3206.26  119.713207.001   127.5 3207.79   135.5 3209.99
   147.5 3211.67   155.6 3210.19   159.6 3210.57   167.6 3216.04   179.6 3221.16
   187.6 3223.13   199.6 3224.24   207.6 3226.79   215.6 3230.57226.2773 3236.92
#Mann= 3 ,-1,0
       0      .1       0   94.62    .045       0  119.71      .1       0
Bank Sta=94.62,119.71
XS Rating Curve= 0 ,0
Exp/Cntr(USF)=0,0
Exp/Cntr=0.3,0.1

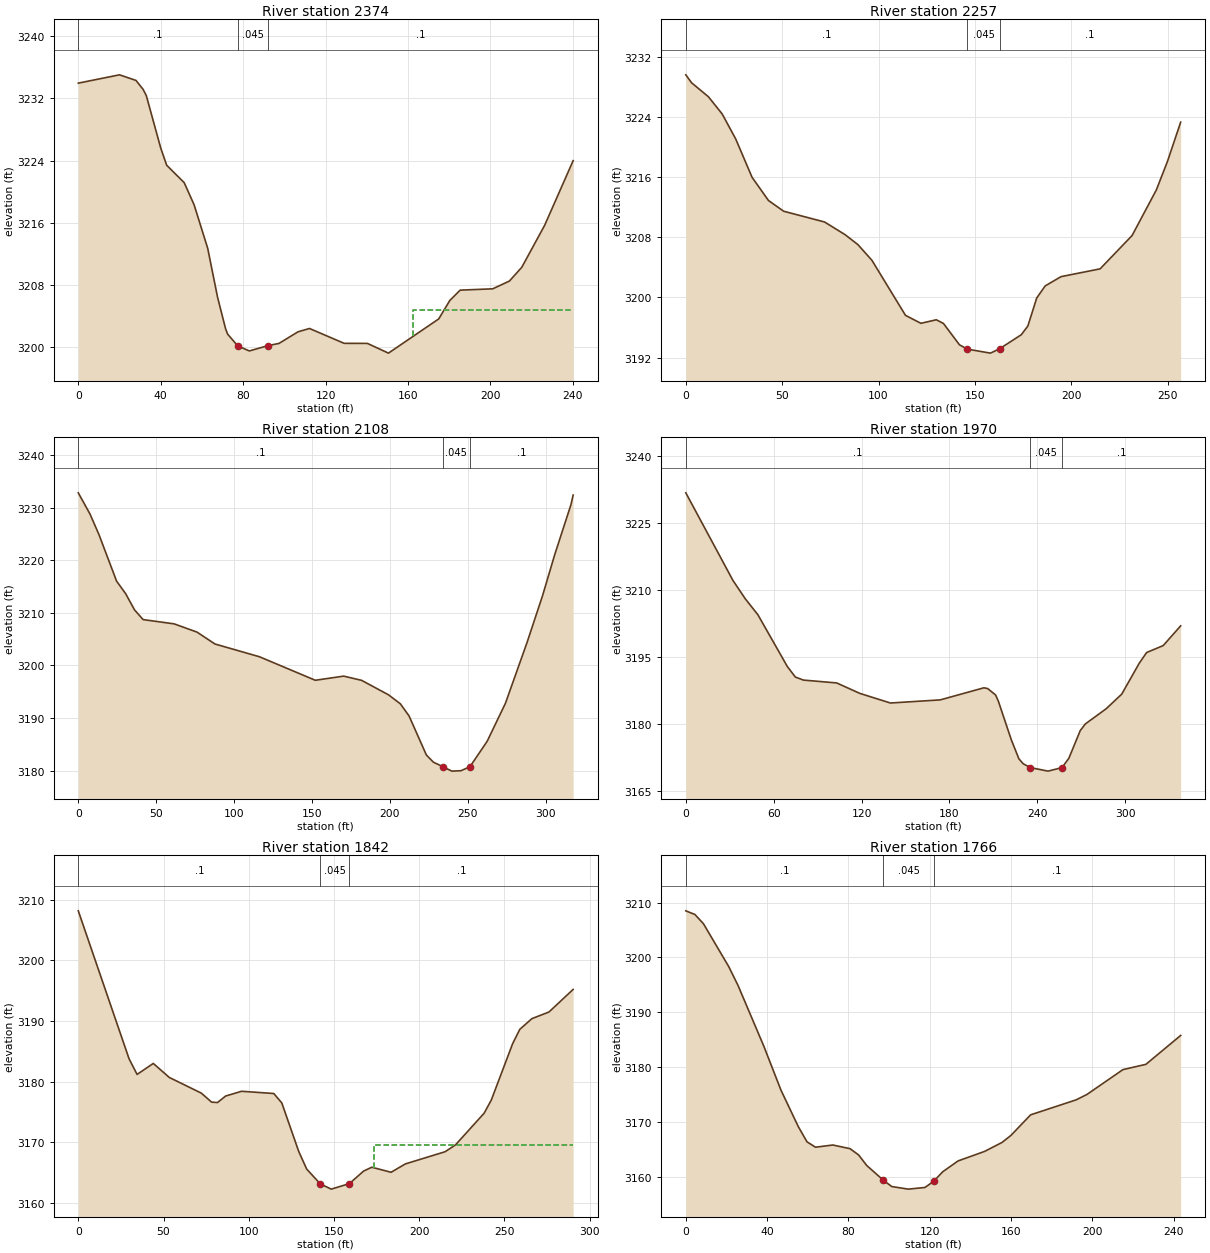
Type RM Length L Ch R = 1 ,2374    ,129.8,116.8,104.2
XS GIS Cut Line= 4
2251254.70375443533958.6803427312251289.12608462534005.075657332
2251340.01126838534078.4101868632251395.38632129534153.241339446
#Sta/Elev= 30
       0 3233.96      20 3235.03      28 3234.31    31.4 3233.18      33 3232.37
      40 3225.62    42.9  3223.4    51.4 3221.16    56.2 3218.32    62.8 3212.72
    67.6 3206.41    71.5 3202.35    72.5 3201.67    77.4 3200.17      83 3199.52
      92  3200.2    97.4 3200.49   106.6 3201.98   112.2 3202.41     129  3200.5
   140.3 3200.49   150.5 3199.24   174.9 3203.64   180.3 3206.02   185.3 3207.34
   201.1 3207.51   209.2 3208.51   215.2 3210.28   226.3 3215.68240.1218 3223.99
#Mann= 3 ,-1,0
       0      .1       0    77.4    .045       0      92      .1       0
#XS Ineff= 2 , 0
                          162.44         3204.78
Permanent Ineff=
       F       F
Bank Sta=77.4,92
XS Rating Curve= 0 ,0
Exp/Cntr(USF)=0,0
Exp/Cntr=0.3,0.1

Type RM Length L Ch R = 1 ,2257    ,138.8,149.5,161.7
XS GIS Cut Line= 5
2251173.88610965534058.954087192 2251237.1411975534113.992622088
2251250.83475592534134.6367642162251336.48529121534128.618919248
2251389.74668967534161.034238827
#Sta/Elev= 30
       0 3229.64       3 3228.58    11.7 3226.73    18.9 3224.42    25.9  3221.1
    34.4 3215.99    42.9 3212.91    50.8 3211.48      72 3210.05    82.6 3208.37
    89.3 3207.04    96.6 3204.94     114 3197.62     122 3196.56     130 3197.03
   133.7 3196.54     142  3193.7   146.1 3193.12   158.1 3192.59  162.82 3193.17
   174.1 3195.04   177.5  3196.2   182.1 3199.93   186.5 3201.54   194.7 3202.77
     215 3203.81   231.6 3208.25   244.2 3214.33     250 3218.15   256.8 3223.34
#Mann= 3 ,0,0
       0      .1       0   146.1    .045       0  162.82      .1       0
Bank Sta=146.1,162.82
XS Rating Curve= 0 ,0
Exp/Cntr(USF)=0,0
Exp/Cntr=0.3,0.1

Type RM Length L Ch R = 1 ,2108    ,138.5,138.1,137.7
XS GIS Cut Line= 4
 2251134.9739103534099.3629095872251250.21388528534217.596130667
2251331.03153007534295.420529353 2251360.9639911534322.359744283
#Sta/Elev= 30
       0 3232.84     7.5 3228.82    13.2 3224.95    24.6 3216.04    30.4 3213.66
    36.1 3210.58    41.6 3208.73    61.5 3207.92    76.2 3206.35    87.7 3204.09
   116.3 3201.66   152.1 3197.19   170.3 3197.98   181.8 3197.18   199.1 3194.42
   206.7 3192.71   212.3 3190.39   223.4 3182.97   227.9 3181.61  233.923180.766
   239.7 3179.91   245.6 3179.99  251.393180.765   262.4 3185.59   274.1  3192.8
   287.9  3204.3   297.9 3213.24   305.7 3221.04   316.2 3230.62317.5709 3232.41
#Mann= 3 ,-1,0
       0      .1       0  233.92    .045       0  251.39      .1       0
Bank Sta=233.92,251.39
XS Rating Curve= 0 ,0
Exp/Cntr(USF)=0,0
Exp/Cntr=0.3,0.1

Type RM Length L Ch R = 1 ,1970    ,124.4,127.9,132.5
XS GIS Cut Line= 4
2251037.69341194534210.1130154092251166.40299439534331.339482593
2251254.70375443534410.6605043312251284.63621547534440.592965364
#Sta/Elev= 30
       0 3231.76    32.2 3212.11    40.7 3207.96    49.2 3204.44    69.3 3192.83
    74.8 3190.46    80.3 3189.78     103 3189.14   118.8  3186.8   139.7 3184.64
   173.7 3185.34   203.5 3188.05   206.1 3187.88   211.5 3186.44   213.4 3185.03
   222.2 3176.41   227.4 3172.12   230.4 3171.01  235.233170.165   247.3 3169.37
  256.843170.164   261.5 3172.25   269.3 3178.47   272.8 3179.96     287 3183.36
   297.6 3186.63   309.6 3193.58   314.6 3195.96   325.9 3197.51 337.838 3201.94
#Mann= 3 ,-1,0
       0      .1       0  235.23    .045       0  256.84      .1       0
Bank Sta=235.23,256.84
XS Rating Curve= 0 ,0
Exp/Cntr(USF)=0,0
Exp/Cntr=0.3,0.1

Type RM Length L Ch R = 1 ,1842    ,84.7,76.1,60.4
XS GIS Cut Line= 4
 2250994.8642144534362.8213524332251099.14730134534427.828991047
2251126.91098034534470.490253887 2251237.9656963534505.702724803
#Sta/Elev= 30
       0 3208.17    29.8 3183.76    34.5 3181.19      44    3183    53.4 3180.69
    72.2  3178.1    78.2 3176.62    81.7 3176.55    86.4 3177.62    95.8 3178.41
   114.7 3178.04   119.4 3176.48   129.3  3168.5     134 3165.57     142 3163.13
   148.4 3162.27  159.04 3163.18   167.4 3165.25   172.2 3165.88   183.5 3165.05
   191.9 3166.43   215.2 3168.44   221.3 3169.57   238.1  3174.8   242.3 3176.97
   254.8 3186.26     259 3188.62   266.1 3190.39   276.1 3191.48   290.3 3195.21
#Mann= 3 ,0,0
       0      .1       0     142    .045       0  159.04      .1       0
#XS Ineff= 2 , 0
                          173.24         3169.48
Permanent Ineff=
       F       F
Bank Sta=142,159.04
XS Rating Curve= 0 ,0
Exp/Cntr(USF)=0,0
Exp/Cntr=0.3,0.1

Type RM Length L Ch R = 1 ,1766    ,109.6,120,129.5
XS GIS Cut Line= 4
2250979.96663055534473.8760683992251059.19469011 534501.63974739
2251110.65907068534511.7971909242251190.56429315534582.899295658
#Sta/Elev= 30
       0 3208.49     4.5 3207.82     8.7 3206.13    21.1 3198.35    25.7  3194.9
    38.4 3183.83    46.8 3175.86    55.3 3169.24    59.6 3166.45    63.8 3165.47
    72.3 3165.87    80.8  3165.2      85 3164.06      89 3162.14    97.2 3159.45
   101.3 3158.31   109.4 3157.84   117.6 3158.14   121.9 3159.26   126.4 3161.01
   133.9 3162.97     147 3164.71   155.5 3166.33   159.9 3167.61   169.6 3171.36
     192 3174.09   197.3 3175.07     215 3179.59   226.3 3180.55   243.4 3185.81
#Mann= 3 ,0,0
       0      .1       0    97.2    .045       0   121.9      .1       0
Bank Sta=97.2,121.9
XS Rating Curve= 0 ,0
Exp/Cntr(USF)=0,0
Exp/Cntr=0.3,0.1

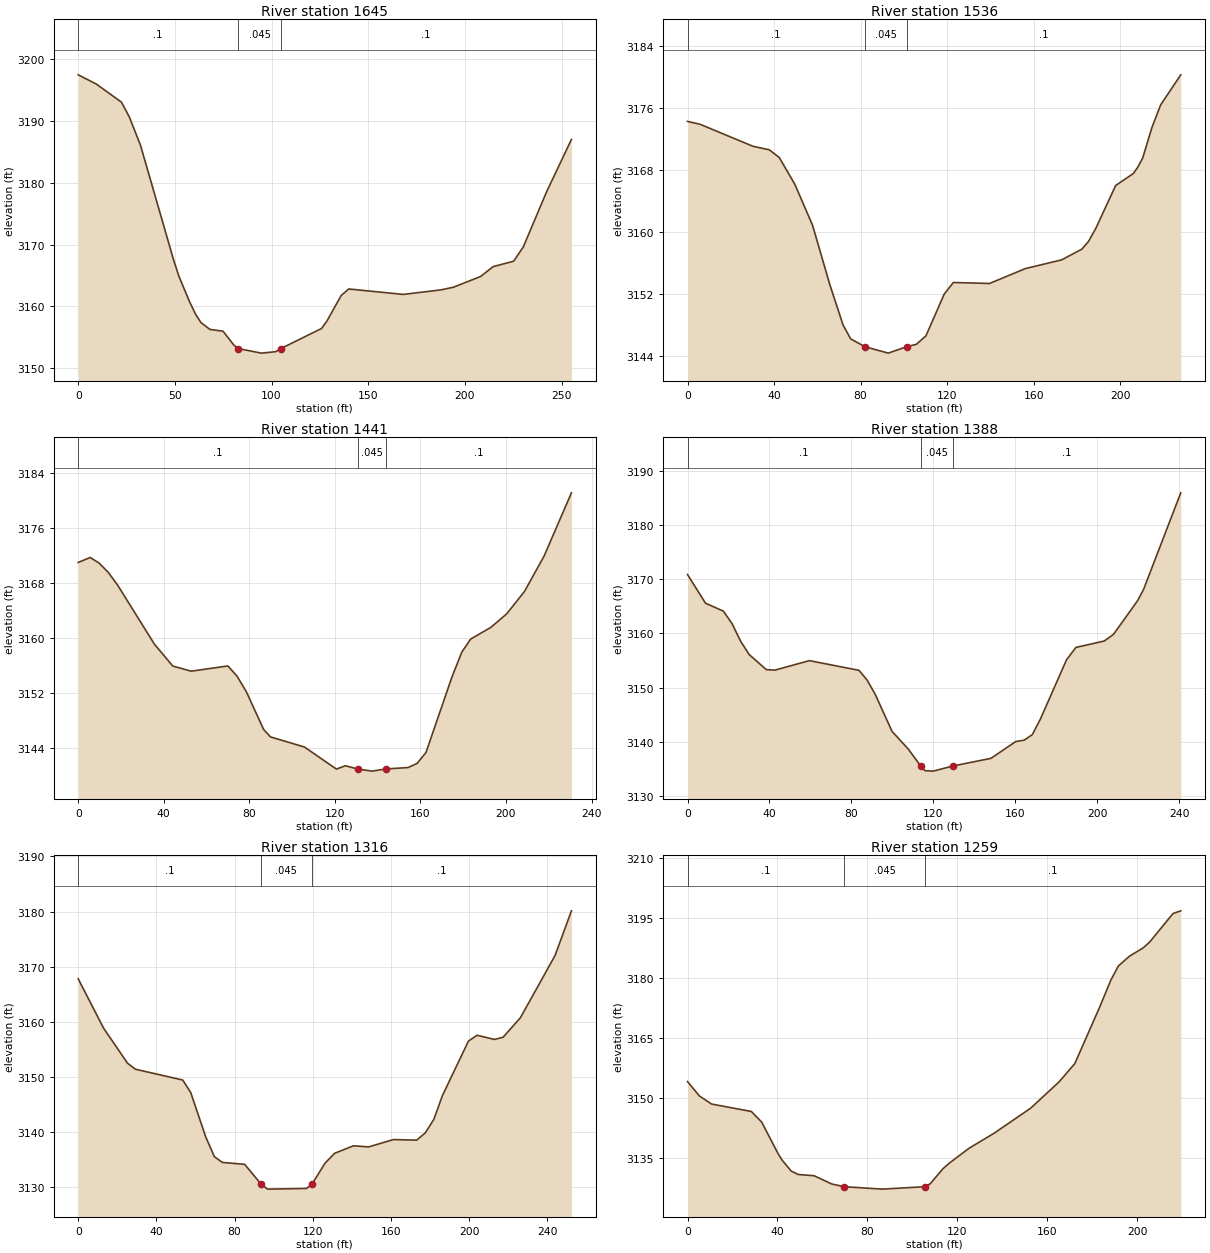
Type RM Length L Ch R = 1 ,1645    ,116.8,109.1,105.2
XS GIS Cut Line= 4
2250946.39940579534537.8734637212250997.28458955534576.785663064
2251057.14951162534636.6505851312251139.46377946534703.998622455
#Sta/Elev= 30
       0 3197.48     9.3    3196    22.4 3193.05    26.5 3190.62    32.2  3186.1
    49.3 3167.57    52.1 3164.87    57.6 3160.76    60.7 3158.75    63.5 3157.39
    68.1 3156.29    74.9    3156    80.5 3153.75   82.793153.189    94.7 3152.45
   102.1 3152.68  104.813153.188   125.8 3156.43   128.6 3157.63     136 3161.77
   139.9 3162.83   168.1 3161.95   187.5 3162.68     194 3163.11   208.1 3164.85
   214.6 3166.45   225.2 3167.32   230.2 3169.65   242.2 3178.53255.0751 3187.03
#Mann= 3 ,-1,0
       0      .1       0   82.79    .045       0  104.81      .1       0
Bank Sta=82.79,104.81
XS Rating Curve= 0 ,0
Exp/Cntr(USF)=0,0
Exp/Cntr=0.3,0.1

Type RM Length L Ch R = 1 ,1536    ,85.6,95.3,106.2
XS GIS Cut Line= 4
2250911.97707561534632.1607159762250940.41291359534683.045899732
 2250993.7862364534705.6427217422251101.09408333534736.948557562
#Sta/Elev= 30
       0 3174.29     5.7 3173.93    30.3 3171.07    37.8 3170.62    42.4 3169.63
    49.6 3166.17    57.8 3160.87    65.8 3153.18    71.9 3147.98    75.4 3146.19
      82 3145.17    92.8 3144.34   101.5 3145.19   105.8 3145.48   110.2 3146.57
   118.7 3151.99   122.9 3153.47   139.6 3153.34   156.2 3155.27   172.9 3156.39
   182.3 3157.78   185.4 3158.79   188.8  3160.5   197.9    3166   206.2 3167.58
   208.1 3168.36   210.4 3169.55   214.6 3173.44   218.7 3176.42     228 3180.31
#Mann= 3 ,0,0
       0      .1       0      82    .045       0   101.5      .1       0
Bank Sta=82,101.5
XS Rating Curve= 0 ,0
Exp/Cntr(USF)=0,0
Exp/Cntr=0.3,0.1

Type RM Length L Ch R = 1 ,1441    ,52,53,55.5
XS GIS Cut Line= 4
2250873.01516825534644.0096857842250904.65527619534724.746512929
 2250930.8401931534808.7564546882250947.20576617534862.217326716
#Sta/Elev= 30
       0 3170.95     5.6 3171.68     9.8 3170.86    14.1  3169.5    18.4 3167.68
    35.6  3159.1    44.2 3155.91    52.8 3155.16      70 3155.92    74.3 3154.42
    78.6 3152.18    86.7 3146.69    89.9 3145.61   105.8 3144.14   120.7 3140.94
   124.9 3141.42   130.7 3140.95   137.4 3140.64     144 3140.96   154.2 3141.16
   158.4 3141.75   162.6 3143.35   174.7 3154.28   179.3  3157.9   183.5 3159.83
   192.9 3161.52   200.3 3163.48   208.6 3166.72   217.8 3171.87   230.6 3181.07
#Mann= 3 ,-1,0
       0      .1       0   130.7    .045       0     144      .1       0
Bank Sta=130.7,144
XS Rating Curve= 0 ,0
Exp/Cntr(USF)=0,0
Exp/Cntr=0.3,0.1

Type RM Length L Ch R = 1 ,1388    ,81.6,71.8,64.6
XS GIS Cut Line= 4
2250841.63579218534648.623569544 2250859.5952688534702.501999403
2250874.56149931534825.2250896392250904.49396035534877.606896447
#Sta/Elev= 30
       0 3170.86     8.8 3165.57    17.5 3164.11    21.7 3161.83    25.9 3158.57
    30.1 3156.09    38.5  3153.3    42.7 3153.22    59.5 3154.97    83.7 3153.18
    87.7 3151.36    91.7 3148.69    99.8 3141.93   107.8 3138.62  113.843135.507
   115.9 3134.66   119.9 3134.57  129.423135.507   148.1 3136.93   160.2 3140.03
   164.3 3140.28   168.3 3141.31   172.3 3144.22     185 3155.13   189.6 3157.41
   203.4 3158.59   207.9 3159.81   219.7 3166.04   222.6 3168.11 240.756 3185.95
#Mann= 3 ,-1,0
       0      .1       0  113.84    .045       0  129.42      .1       0
Bank Sta=113.84,129.42
XS Rating Curve= 0 ,0
Exp/Cntr(USF)=0,0
Exp/Cntr=0.3,0.1

Type RM Length L Ch R = 1 ,1316    ,56.6,57.1,57.9
XS GIS Cut Line= 5
2250770.04613086534676.347776166  2250782.912226534755.575835727
 2250814.0617195534799.5914243722250849.27419042534806.363053394
2250884.48666134 534880.85097264
#Sta/Elev= 30
       0 3167.82      13 3158.87    25.2 3152.54    29.2 3151.44    53.5 3149.47
    57.6 3147.19    65.3 3139.13    69.7 3135.58    73.8 3134.54    85.2 3134.19
    93.5 3130.64    96.9  3129.7   116.8 3129.82   119.6 3130.58   126.3  3134.4
   131.2 3136.19   140.8 3137.55   148.6 3137.35   161.3 3138.68   173.2 3138.58
   177.6 3139.89     182 3142.35   186.4 3146.67   199.7 3156.53   204.1 3157.59
     213 3156.83   217.4 3157.22   226.3 3160.77     244 3172.03   252.4 3180.14
#Mann= 3 ,0,0
       0      .1       0    93.5    .045       0   119.6      .1       0
Bank Sta=93.5,119.6
XS Rating Curve= 0 ,0
Exp/Cntr(USF)=0,0
Exp/Cntr=0.3,0.1

Type RM Length L Ch R = 1 ,1259    ,110.7,106.7,103.7
XS GIS Cut Line= 4
2250700.95322532534748.8973140052250735.37555551534786.312890296
2250802.72359284 534880.600142552250832.65605387534924.002211048
#Sta/Elev= 30
       0  3154.1     5.3  3150.5    10.7 3148.49    28.4 3146.63      33 3143.98
    40.2 3136.21    42.1 3134.48    46.1 3131.77    49.3  3130.9    56.3  3130.6
    64.2 3128.53   69.613127.861    86.6 3127.25  105.71 3127.86     108  3128.6
   113.7 3132.38   116.6 3133.79   125.2 3137.43   136.6 3141.28   152.7 3147.47
   165.3 3154.02   172.3 3158.58   183.4 3172.72   188.3 3179.38   191.7 3182.95
   196.6 3185.38   202.7 3187.45   205.6 3188.91     216 3196.04219.4339 3196.71
#Mann= 3 ,0,0
       0      .1       0   69.61    .045       0  105.71      .1       0
Bank Sta=69.61,105.71
XS Rating Curve= 0 ,0
Exp/Cntr(USF)=0,0
Exp/Cntr=0.3,0.1

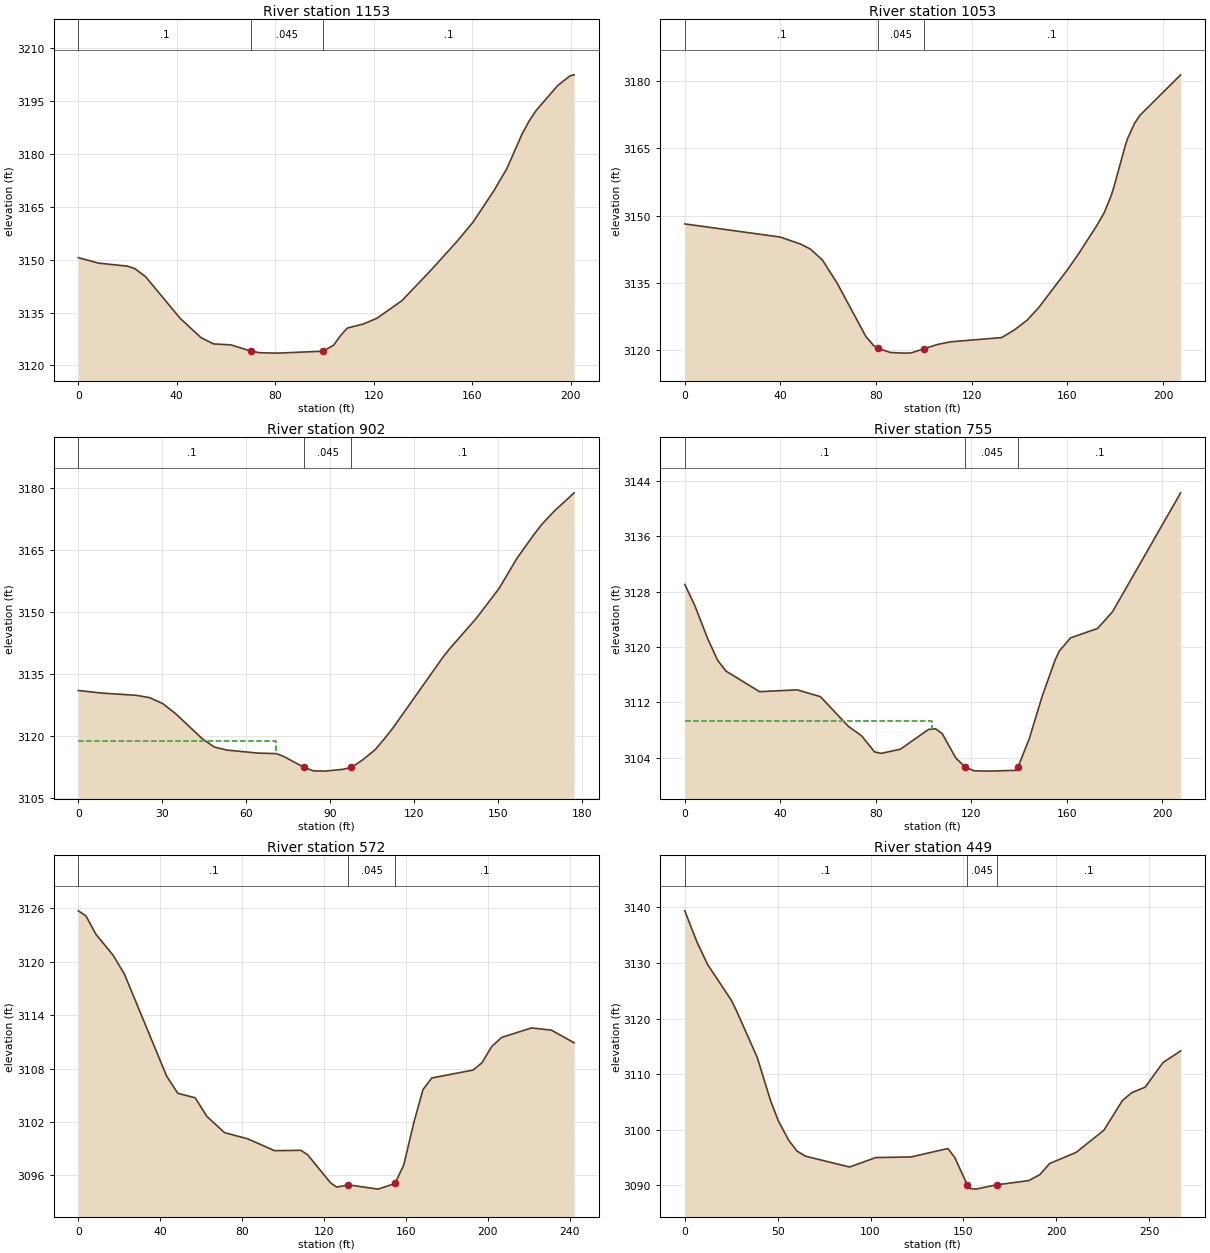
Type RM Length L Ch R = 1 ,1153    ,100.7,99.1,100.1
XS GIS Cut Line= 4
2250623.12882664534835.7014510012250656.05453377534865.633912034
2250721.90594805 534934.478572412250760.81814739534982.370510063
#Sta/Elev= 30
       0 3150.56     8.1 3149.02      20 3148.14      23 3147.42    27.3 3145.18
    41.4 3133.34    49.9 3127.86    54.9 3126.11      62 3125.82   70.313124.045
    73.6 3123.61      81 3123.49   99.453124.045   103.7 3125.72   106.5 3128.42
   109.3 3130.59   115.8 3131.74   121.4  3133.4   131.5 3138.37   143.3 3147.02
   153.6 3154.95   160.4 3160.64   168.9 3169.58   174.2 3175.91   180.3 3185.59
   183.1  3189.2     186 3192.27   194.8 3199.36   199.9 3202.15201.4732 3202.39
#Mann= 3 ,-1,0
       0      .1       0   70.31    .045       0   99.45      .1       0
Bank Sta=70.31,99.45
XS Rating Curve= 0 ,0
Exp/Cntr(USF)=0,0
Exp/Cntr=0.3,0.1

Type RM Length L Ch R = 1 ,1053    ,158.1,151,149.5
XS GIS Cut Line= 3
2250573.66888921534876.7879952272250577.73186663534930.961027405
 2250692.1723971 535032.53546274
#Sta/Elev= 30
       0 3148.13      40  3145.2    48.5 3143.62    52.5 3142.54    57.6 3140.06
    63.7 3134.94    75.7 3123.08      79 3121.03    80.9 3120.41      86 3119.51
    91.6 3119.37    94.5  3119.4    99.8 3120.31   105.8 3121.32   111.1 3121.89
   132.5 3122.83   137.8 3124.53   143.2 3126.73   148.1 3129.59   160.1 3138.01
   164.6 3141.45   172.2 3147.72   175.3 3150.57   178.2 3154.32   179.5 3156.54
   184.2 3165.64   185.1  3167.1     188 3170.49   190.2 3172.26   207.3 3181.32
#Mann= 3 ,0,0
       0      .1       0    80.9    .045       0    99.8      .1       0
Bank Sta=80.9,99.8
XS Rating Curve= 0 ,0
Exp/Cntr(USF)=0,0
Exp/Cntr=0.3,0.1

Type RM Length L Ch R = 1 ,902     ,141.3,147.5,153.9
XS GIS Cut Line= 4
2250486.93612894535058.6982856972250521.35845912535081.147631472
2250600.67948086535118.5632077632250642.58492631 535142.50917659
#Sta/Elev= 30
       0    3131     8.5 3130.37    20.6 3129.84    25.4 3129.28    30.1 3127.86
    34.9  3125.3    44.2 3119.36    48.6  3117.3    53.1 3116.57    64.3 3115.84
    70.7 3115.72    73.3 3115.05   80.683112.366      84 3111.54      88 3111.48
    94.3  3111.9   97.493112.365   101.7 3114.28   106.1 3116.74   109.3 3119.31
   112.4 3121.98   130.3 3139.15   132.8 3141.27   142.1 3148.46   150.2 3155.67
   156.7 3163.06   162.6 3168.67   165.5 3171.21   169.7 3174.26177.0631 3178.86
#Mann= 3 ,-1,0
       0      .1       0   80.68    .045       0   97.49      .1       0
#XS Ineff= 2 , 0
           70.63  3118.8
Permanent Ineff=
       F       F
Bank Sta=80.68,97.49
XS Rating Curve= 0 ,0
Exp/Cntr(USF)=0,0
Exp/Cntr=0.3,0.1

Type RM Length L Ch R = 1 ,755     ,180.4,183.4,186.3
XS GIS Cut Line= 4
2250409.11173025535144.0057996422250467.48002926 535196.38760645
2250525.84832828535260.7423976712250557.27741236535289.178235652
#Sta/Elev= 30
       0 3129.03     4.1 3126.06     9.5 3121.27    13.7 3118.09    17.2 3116.52
    31.3 3113.53    47.1 3113.79    56.8 3112.81    68.6 3108.49      74 3107.17
    79.5 3104.81    82.3 3104.61    90.3 3105.21   102.1 3108.07     105 3108.17
   107.8 3107.48   113.5 3103.95  117.443102.632   121.1 3102.09   127.6 3102.04
   138.9 3102.16  139.583102.631   144.3 3106.73   149.7 3112.87   155.1 3118.09
   156.9 3119.42   161.6 3121.31   172.9 3122.67   179.2  3125.1207.6918 3142.28
#Mann= 3 ,-1,0
       0      .1       0  117.44    .045       0  139.58      .1       0
#XS Ineff= 2 , 0
          103.41 3109.32
Permanent Ineff=
       F       F
Bank Sta=117.44,139.58
XS Rating Curve= 0 ,0
Exp/Cntr(USF)=0,0
Exp/Cntr=0.3,0.1

Type RM Length L Ch R = 1 ,572     ,126.2,122.3,117.6
XS GIS Cut Line= 4
2250269.92578645535223.3268213792250328.29408546535299.654597014
2250371.69615396535369.995880442 2250407.6151072535422.377687249
#Sta/Elev= 30
       0 3125.72     3.7 3125.16     8.6 3123.08    16.9 3120.76    22.5 3118.62
    43.2 3107.12    48.6 3105.22    57.1 3104.71    62.8 3102.63    71.4  3100.8
    82.8  3100.1    95.9 3098.77   108.7 3098.81     112 3098.32   123.3 3095.14
   126.3 3094.68     132 3094.93   146.5 3094.45   154.73095.084     159 3097.17
     164 3101.99   168.4 3105.63   172.7 3106.94   192.9 3107.83   197.2 3108.65
     202 3110.48   206.9  3111.5   221.4 3112.56   231.1 3112.32242.2551 3110.89
#Mann= 3 ,-1,0
       0      .1       0     132    .045       0   154.7      .1       0
Bank Sta=132,154.7
XS Rating Curve= 0 ,0
Exp/Cntr(USF)=0,0
Exp/Cntr=0.3,0.1

Type RM Length L Ch R = 1 ,449     ,157.6,165.9,172.7
XS GIS Cut Line= 4
2250138.56288523535297.4169924792250227.87987656535387.795959212
2250280.57320751535432.4225566412250337.22977627535474.915475544
#Sta/Elev= 30
       0  3139.4     6.6 3133.75    12.3 3129.73    25.1 3123.28    27.8 3121.44
      39 3113.01    46.2 3105.21    50.3 3101.66    55.9 3098.12    60.4 3096.17
    64.9 3095.25    88.7  3093.3   102.8    3095   121.8 3095.11   141.6 3096.63
   145.3 3095.04     152 3090.12   153.8 3089.42   156.6 3089.32     168  3090.1
   185.1 3090.85   191.1 3091.92   196.4 3093.93   210.7 3095.94   225.6 3099.92
   235.6 3105.28   240.6 3106.67   247.8 3107.67   257.4 3112.09   266.9 3114.19
#Mann= 3 ,-1,0
       0      .1       0     152    .045       0     168      .1       0
Bank Sta=152,168
XS Rating Curve= 0 ,0
Exp/Cntr(USF)=0,0
Exp/Cntr=0.3,0.1