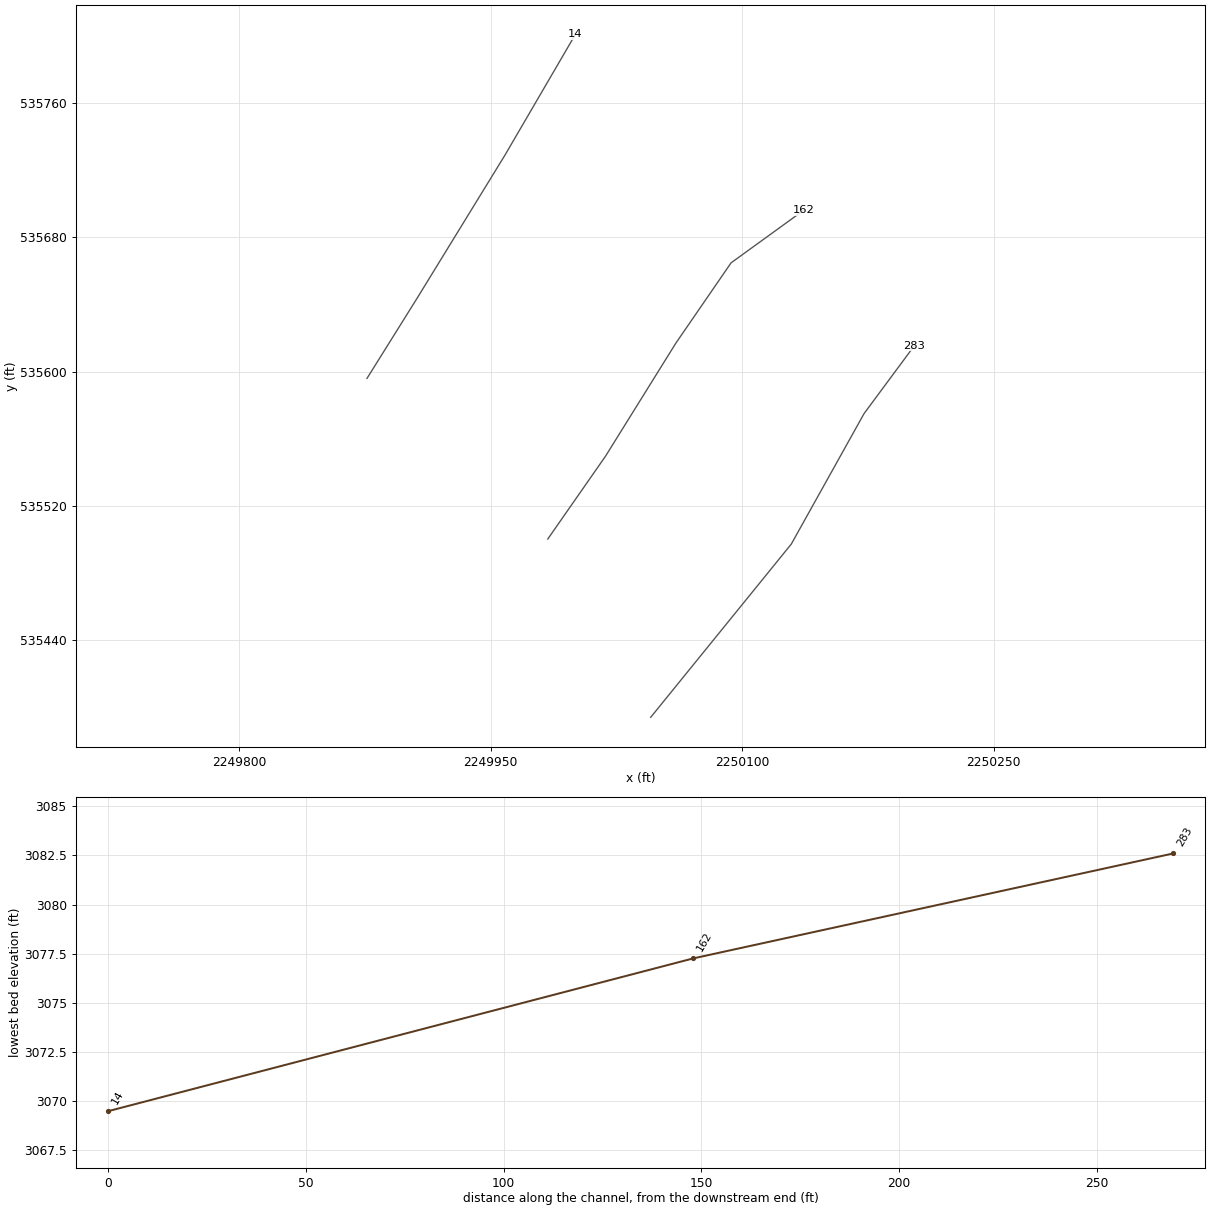
HEC-RAS study TYGRTVALRV.prj: TYGRTVALRV

--- TYGRTVALRV.g01 (geometry) --- (continued)

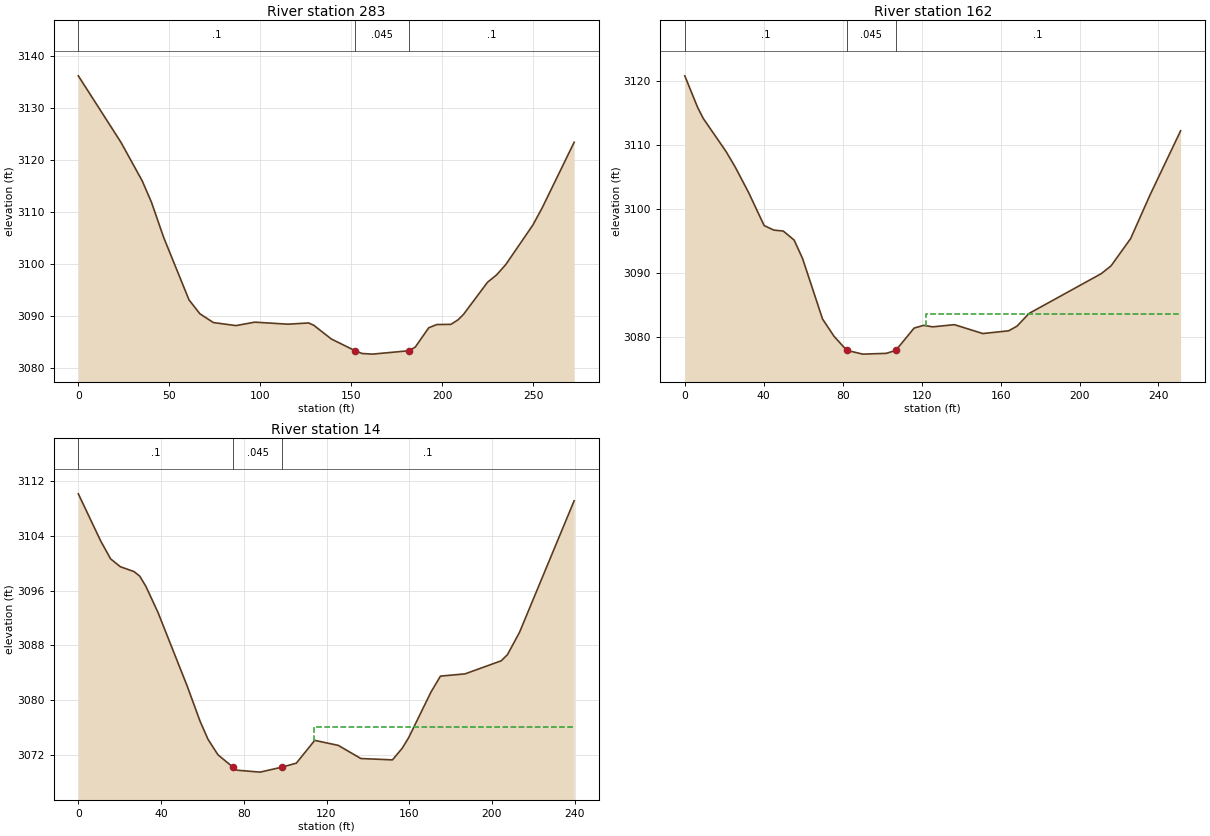
Type RM Length L Ch R = 1 ,283     ,121.9,121.4,120.4
XS GIS Cut Line= 4
 2250045.4323287535393.9418492682250129.24321959535497.208839832
2250172.64528809535575.0332385182250202.57774912535615.442060913
#Sta/Elev= 30
       0 3136.14    23.4 3123.36    35.1 3115.93    40.2  3111.8    46.9 3105.04
    60.8 3093.04    66.8 3090.36    74.2 3088.67    86.6 3088.09    96.9 3088.75
   115.2 3088.36   126.5  3088.6   129.4 3088.14     139 3085.51  152.033083.255
   155.9 3082.72   161.6  3082.6  181.763083.255   185.1 3083.95   192.5 3087.67
   196.9 3088.29   204.7 3088.33   208.6  3089.2   211.6 3090.24   224.8 3096.43
   229.8 3097.85   234.8 3099.82   249.7 3107.43   254.8 3110.72272.3937 3123.36
#Mann= 3 ,-1,0
       0      .1       0  152.03    .045       0  181.76      .1       0
Bank Sta=152.03,181.76
XS Rating Curve= 0 ,0
Exp/Cntr(USF)=0,0
Exp/Cntr=0.3,0.1

Type RM Length L Ch R = 1 ,162     ,147.8,147.9,147.8
XS GIS Cut Line= 5
2249984.07078358535500.2020859362250018.49311377 535549.59064664
2250060.39855921535616.9386839652250093.32426635535664.830621618
2250136.72633485535696.259705702
#Sta/Elev= 30
       0 3120.81     6.5 3115.87     9.4 3114.12    20.9 3108.97    25.6 3106.51
    32.4 3102.51    40.2 3097.38    45.1 3096.67    49.9 3096.52    55.4 3095.11
    59.7  3092.2    69.8 3082.75    75.6 3080.06   82.063077.853    90.2 3077.26
   102.1 3077.38  106.943077.854   116.2 3081.34     121 3081.76   125.7 3081.53
   136.6 3081.87     151 3080.48   164.1 3080.91   168.3 3081.63   174.4 3083.62
     211 3089.85     216 3091.08   225.9 3095.34   235.7 3102.15251.2267 3112.21
#Mann= 3 ,-1,0
       0      .1       0   82.06    .045       0  106.94      .1       0
#XS Ineff= 2 , 0
                          122.44         3083.55
Permanent Ineff=
       F       F
Bank Sta=82.06,106.94
XS Rating Curve= 0 ,0
Exp/Cntr(USF)=0,0
Exp/Cntr=0.3,0.1

Type RM Length L Ch R = 1 ,14      ,,,
XS GIS Cut Line= 4
2249876.31392386535595.9859612412249906.24638489535643.877898894
 2249958.6281917535729.1854128392250000.53363715535801.023319318
#Sta/Elev= 30
       0 3110.16    10.8 3103.28    15.6 3100.66    20.3 3099.51    26.9  3098.8
    29.7 3098.13    32.7 3096.62    38.5 3092.84    52.6  3082.1    58.8 3076.98
    62.7 3074.29    67.5 3072.03   74.743070.223    76.8 3069.77    87.9 3069.49
   98.543070.224   105.4  3070.8   114.3 3074.13   125.7  3073.4   136.6 3071.48
   151.9 3071.28   156.6 3072.98   159.7 3074.51   170.5 3081.18   175.1 3083.52
     187 3083.85   204.5 3085.76   207.5 3086.66   213.3  3089.9239.7495 3109.15
#Mann= 3 ,-1,0
       0      .1       0   74.74    .045       0   98.54      .1       0
#XS Ineff= 2 , 0
                          114.14         3076.09
Permanent Ineff=
       F       F
Bank Sta=74.74,98.54
XS Rating Curve= 0 ,0
Exp/Cntr(USF)=0,0
Exp/Cntr=0.3,0.1
LCMann Table=0

Chan Stop Cuts=-1
Use User Specified Reach Order=0
Composite Channel Slope=5